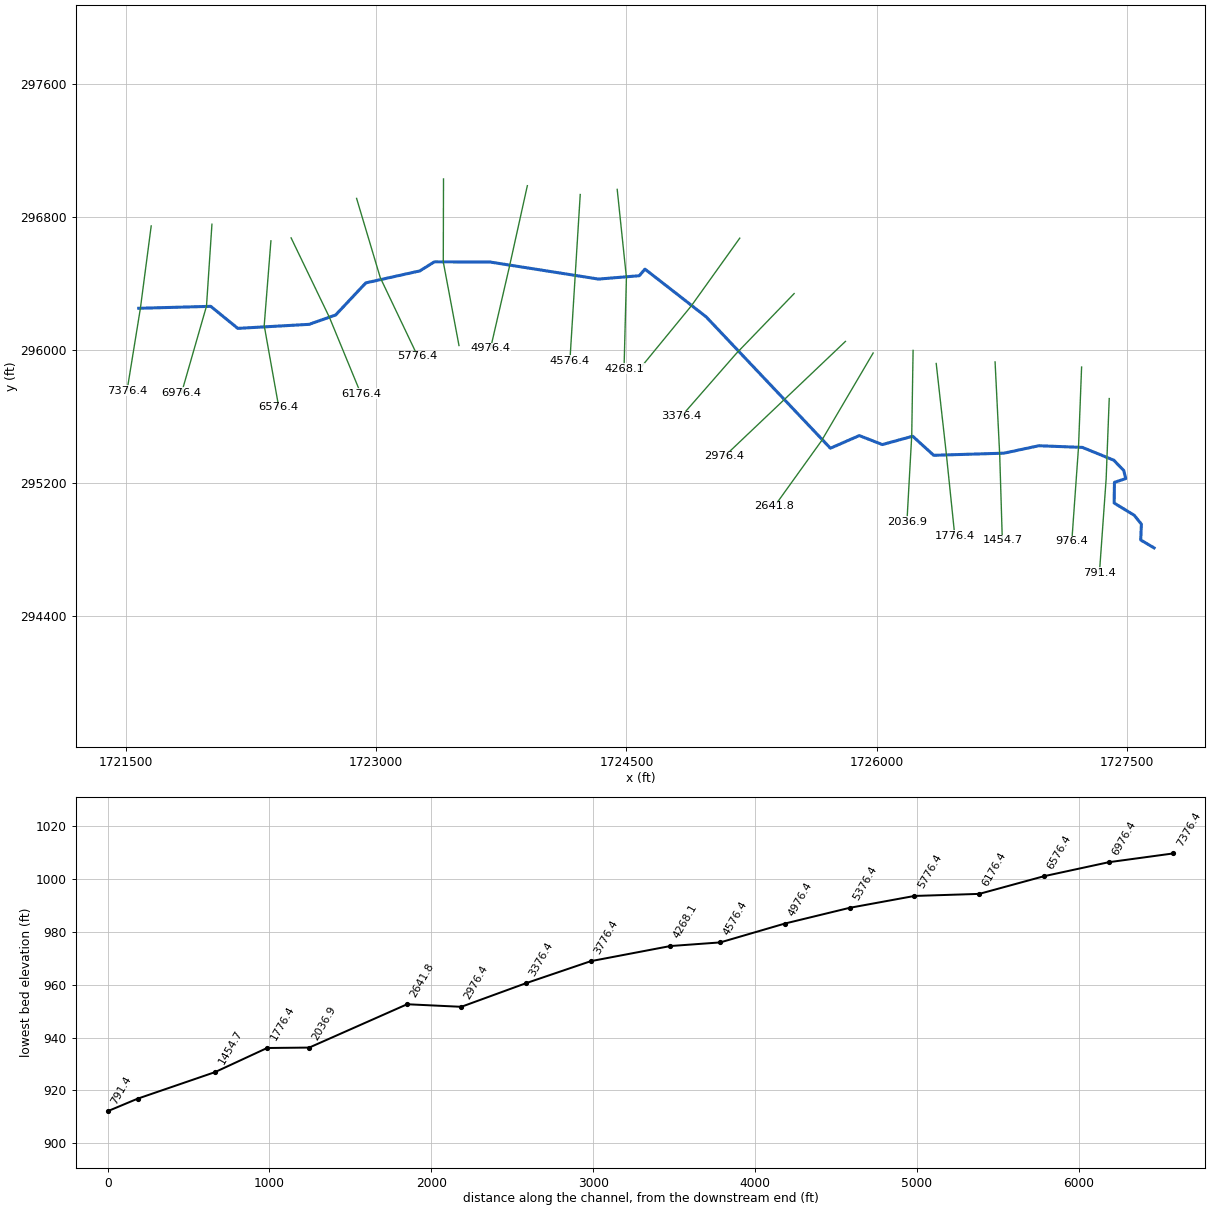
--- KtLckRnTr.prj (project) ---

Proj Title=KtLckRnTr
Current Plan=p01
Default Exp/Contr=0,0
English Units
Geom File=g01
Flow File=f01
Plan File=p01
BEGIN DESCRIPTION:
END DESCRIPTION:
DSS Export Rating Curves= 0
DSS Export Rating Curve Sorted= 0
DSS Export Volume Flow Curves= 0
DXF OffsetX= 0
DXF OffsetY= 0
DXF ScaleX= 0
DXF ScaleY= 0

--- KtLckRnTr.p01 (plan) ---

Plan Title=Floodplain
Program Version=4.00
Geom File=g01
Flow File=f01
K Sum by GR=0
Std Step Tol=0.01
Critical Tol=0.01
Num of Std Step Trials=20
Max Error Tol=0.3
Flow Tol Ratio=0.001
Split Flow NTrial=30
Split Flow Tol=0.02
Split Flow Ratio=0.02
Log Output Level=0
Friction Slope Method=1
Unsteady Friction Slope Method=2
Unsteady Bridges Friction Slope Method=1
Global Log Level=0
CheckData=False
Run HTab=0
Run UNet=0
Run PostProcess=0
UNET Theta=0
UNET Theta Warmup=0
UNET ZTol=0
UNET ZSATol=0
UNET MxIter=0
UNET MaxInSteps=0
UNET DtIC=0
UNET DtMin=0
UNET MaxCRTS=0
UNET WFStab=0
UNET SFStab=0
UNET WFX=0
UNET SFX=0
UNET DSS MLevel=0
UNET DZMax Abort=0
UNET Convert EG Bridges=0
UNET Use Existing IB Tables=0
UNET Froude Limit=0
UNET Froude Power=0
Write IC File=0
Echo Input=False
Echo Output=False
Write Detailed=0

--- KtLckRnTr.f01 (steady flow) ---

Flow Title=NFF Regression Equation
Program Version=4.00
Number of Profiles= 1
Profile Names=P100yr
River Rch & RM=KtLckRnTr,Main            ,7376.4
730.5429
River Rch & RM=KtLckRnTr,Main            ,5776.4
784.4978
River Rch & RM=KtLckRnTr,Main            ,4268.1
836.0263
River Rch & RM=KtLckRnTr,Main            ,3776.4
954.5188
River Rch & RM=KtLckRnTr,Main            ,2036.9
 1016.92
River Rch & RM=KtLckRnTr,Main            ,1776.4
1199.365
Boundary for River Rch & Prof#=KtLckRnTr,Main            , 1
Up Type= 0
Dn Type= 3
Dn Slope=0.0198
DSS Import GetInterval= 0
DSS Import GetPeak= 0
DSS Import FillOption= 0

--- KtLckRnTr.g01 (geometry) ---

Geom Title=USGS 3m DEM
Program Version=4.00

River Reach=KtLckRnTr     ,Main
Reach XY= 30
     1721575.407      296249.123     1722007.441      296260.788
     1722169.604      296128.339     1722597.108      296152.589
     1722756.314      296208.687     1722937.300      296401.686
     1723261.368      296473.727     1723348.349      296528.154
     1723682.185      296527.183     1724332.879      296424.647
     1724577.137      296444.779     1724611.605      296484.484
     1724978.058      296197.982     1725723.440      295408.046
     1725896.635      295483.973     1726034.837      295430.049
     1726216.829      295480.205     1726343.048      295365.499
     1726764.009      295378.348     1726973.513      295422.970
     1727234.760      295412.954     1727422.673      295336.280
     1727482.202      295274.736     1727494.718      295225.845
     1727426.832      295202.886     1727425.153      295078.641
     1727545.777      295005.007     1727588.517      294951.748
     1727584.393      294856.442     1727664.458      294809.281

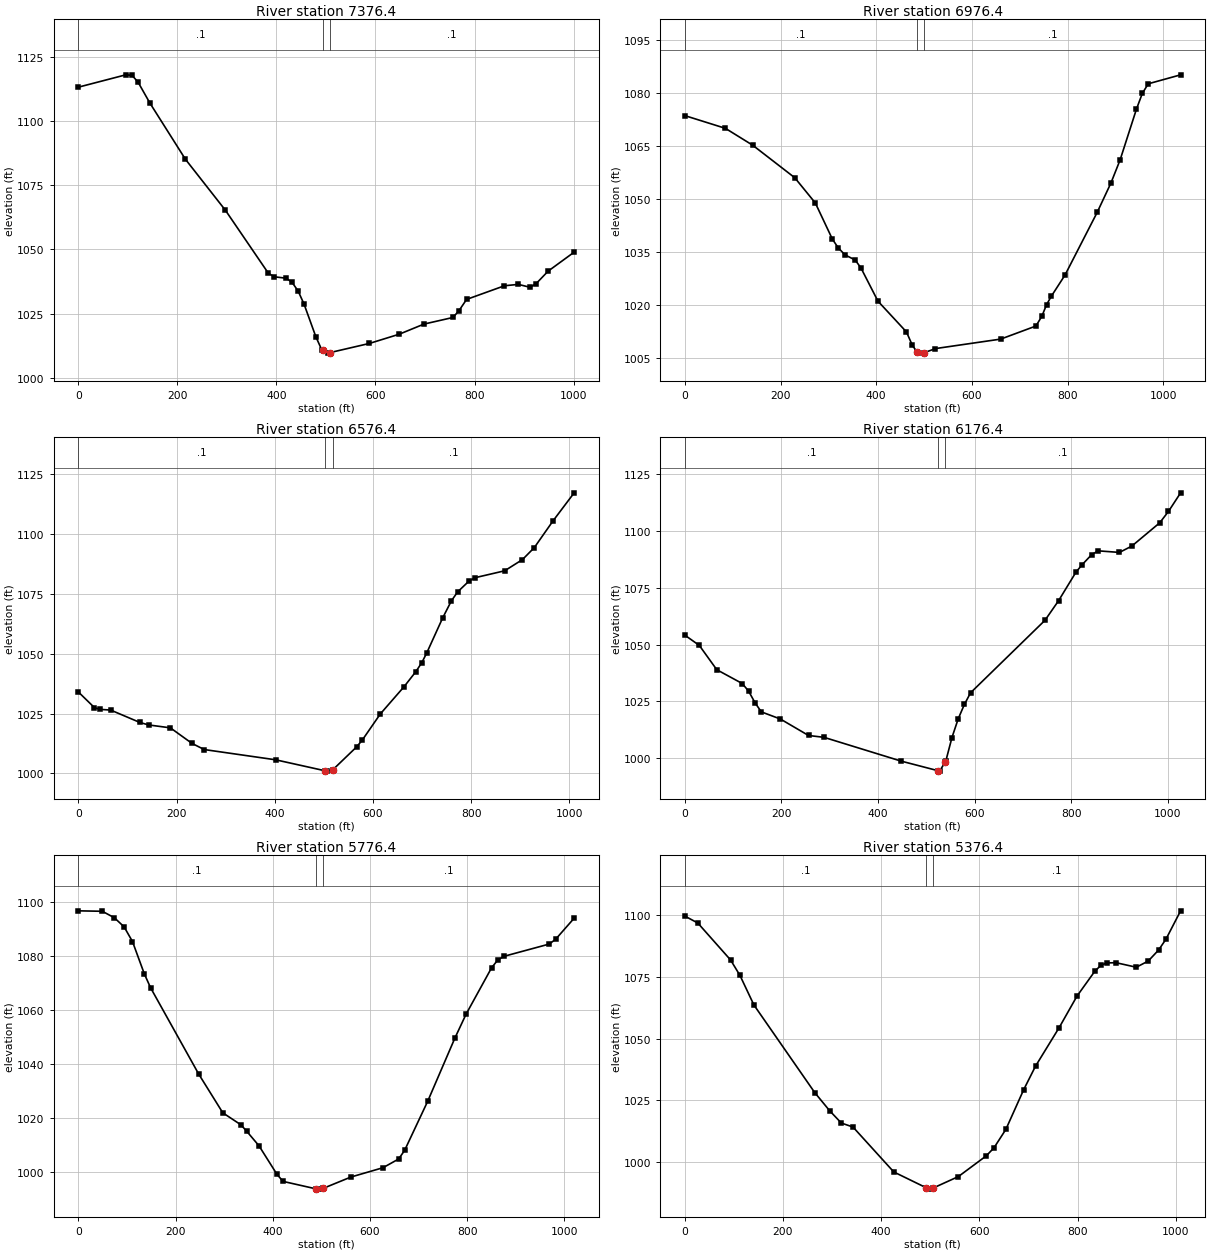
Type RM Length L Ch R = 1 ,7376.4,398.525,400,397.286
XS GIS Cut Line= 3
     1721650.316      296744.064     1721585.279      296247.524
     1721505.294      295753.509
#Sta/Elev= 30
       0 1113.19    95.8 1118.00   108.5 1117.80   120.5 1115.19   144.5 1107.00
   216.3 1085.10   297.0 1065.25   383.9 1040.67   395.9 1039.34   419.9 1038.78
   431.8 1037.12   443.8 1033.80   455.8 1028.69   479.7 1015.94   491.7 1010.83
   493.3 1010.69   503.7 1009.61   508.3 1009.82   587.9 1013.39   648.0 1016.98
   697.9 1020.92   756.3 1023.49   768.3 1026.06   784.0 1030.53   860.5 1035.85
   888.6 1036.38   912.3 1035.24   924.6 1036.71   948.7 1041.55  1001.2 1048.94
#Mann= 3 , 0 , 0
       0     0.1       0   493.3   0.045       0   508.3     0.1       0
Bank Sta=   493.3,   508.3
Exp/Cntr=0.3,0.1

Type RM Length L Ch R = 1 ,6976.4,400.453,400,410.336
XS GIS Cut Line= 3
     1722014.537      296754.353     1721981.972      296262.474
     1721832.220      295740.273
#Sta/Elev= 30
       0 1073.50    84.8 1069.90   142.0 1065.11   229.8 1055.92   272.8 1048.77
   308.5 1038.52   320.4 1036.13   334.7 1034.09   356.1 1032.63   368.0 1030.42
   403.7 1020.98   463.2 1012.28   475.4 1008.54   485.5 1006.56   487.6 1006.28
   500.5 1006.41   523.9 1007.57   660.2 1010.25   733.8 1013.95   746.2 1016.72
   756.2 1020.04   765.8 1022.34   794.6 1028.38   861.8 1046.11   890.6 1054.44
   909.8 1060.99   943.8 1075.30   956.1 1079.77   968.5 1082.50  1036.2 1085.04
#Mann= 3 , 0 , 0
       0     0.1       0   485.5   0.045       0   500.5     0.1       0
Bank Sta=   485.5,   500.5
Exp/Cntr=0.3,0.1

Type RM Length L Ch R = 1 ,6576.4,387.929,400,404.837
XS GIS Cut Line= 3
     1722368.257      296654.480     1722328.009      296145.417
     1722415.497      295654.189
#Sta/Elev= 30
       0 1034.05    32.9 1027.48    43.9 1026.77    65.7 1026.49   125.3 1021.31
   143.2 1020.27   187.4 1019.06   231.5 1012.56   256.3 1010.00   401.7 1005.72
   503.2 1001.10   506.4 1000.99   518.2 1001.56   566.6 1011.10   578.0 1013.90
   614.9 1024.86   663.1 1036.20   687.2 1042.51   699.3 1046.25   709.2 1050.22
   741.7 1064.88   759.6 1072.07   772.4 1075.83   795.8 1080.39   807.8 1081.74
   868.1 1084.62   904.3 1089.30   928.4 1094.29   966.9 1105.55  1009.6 1117.17
#Mann= 3 , 0 , 0
       0     0.1       0   503.2   0.045       0   518.2     0.1       0
Bank Sta=   503.2,   518.2
Exp/Cntr=0.3,0.1

Type RM Length L Ch R = 1 ,6176.4,403.604,400,401.197
XS GIS Cut Line= 3
     1722489.296      296672.320     1722719.534      296193.573
     1722907.708      295735.652
#Sta/Elev= 30
       0 1054.17    30.0 1049.65    66.2 1038.95   118.9 1032.87   132.0 1029.54
   145.6 1024.32   158.4 1020.39   197.9 1017.24   256.1 1010.00   288.0 1009.19
   447.8  998.72   523.7  994.52   527.3  994.31   538.7  998.16   540.2  998.70
   553.0 1009.10   565.9 1017.32   578.7 1023.66   591.5 1028.79   745.6 1060.71
   773.7 1069.33   809.8 1081.93   822.6 1085.21   842.2 1089.60   855.6 1091.27
   899.6 1090.57   925.3 1093.36   983.0 1103.60  1001.2 1108.63  1026.3 1116.80
#Mann= 3 , 0 , 0
       0     0.1       0   523.7   0.045       0   538.7     0.1       0
Bank Sta=   523.7,   538.7
Exp/Cntr=0.3,0.1

Type RM Length L Ch R = 1 ,5776.4,406.679,400,394.119
XS GIS Cut Line= 3
     1722882.068      296909.404     1723023.884      296433.657
     1723248.501      295960.748
#Sta/Elev= 30
       0 1096.70    49.4 1096.53    74.2 1094.12    94.2 1090.75   111.4 1085.31
   135.7 1073.36   148.6 1068.19   247.7 1036.16   297.2 1021.82   334.4 1017.38
   346.8 1014.90   371.6 1009.60   408.7     999   421.1  996.40   488.9  993.63
   495.4  993.53   503.9  993.83   560.7  998.01   626.8 1001.47   659.0 1004.71
   671.3 1007.92   718.8 1026.14   774.8 1049.59   797.7 1058.40   850.3 1075.64
   863.4 1078.59   876.5 1079.88   968.5 1084.37   981.7 1086.12  1020.0 1093.97
#Mann= 3 , 0 , 0
       0     0.1       0   488.9   0.045       0   503.9     0.1       0
Bank Sta=   488.9,   503.9
Exp/Cntr=0.3,0.1

Type RM Length L Ch R = 1 ,5376.4,404.857,400,390.651
XS GIS Cut Line= 3
     1723403.318      297026.569     1723401.868      296527.998
     1723496.062      296025.329
#Sta/Elev= 30
       0 1099.68    26.5 1096.86    93.3 1081.88   112.4 1075.62   140.8 1063.65
   264.6 1028.19   295.1 1020.80   318.9 1015.82   342.6 1014.21   425.7  996.01
   491.1  989.67   497.0  989.05   506.1  989.51   557.3  994.14   614.0 1002.52
   629.8 1005.78   654.0 1013.25   690.2 1029.29   714.4 1038.86   762.7 1054.53
   798.9 1067.25   835.2 1077.32   847.3 1079.67   859.3 1080.69   878.5 1080.78
   919.7 1078.95   943.9 1081.44   965.1 1085.91   980.1 1090.30  1010.0 1101.80
#Mann= 3 , 0 , 0
       0     0.1       0   491.1   0.045       0   506.1     0.1       0
Bank Sta=   491.1,   506.1
Exp/Cntr=0.3,0.1

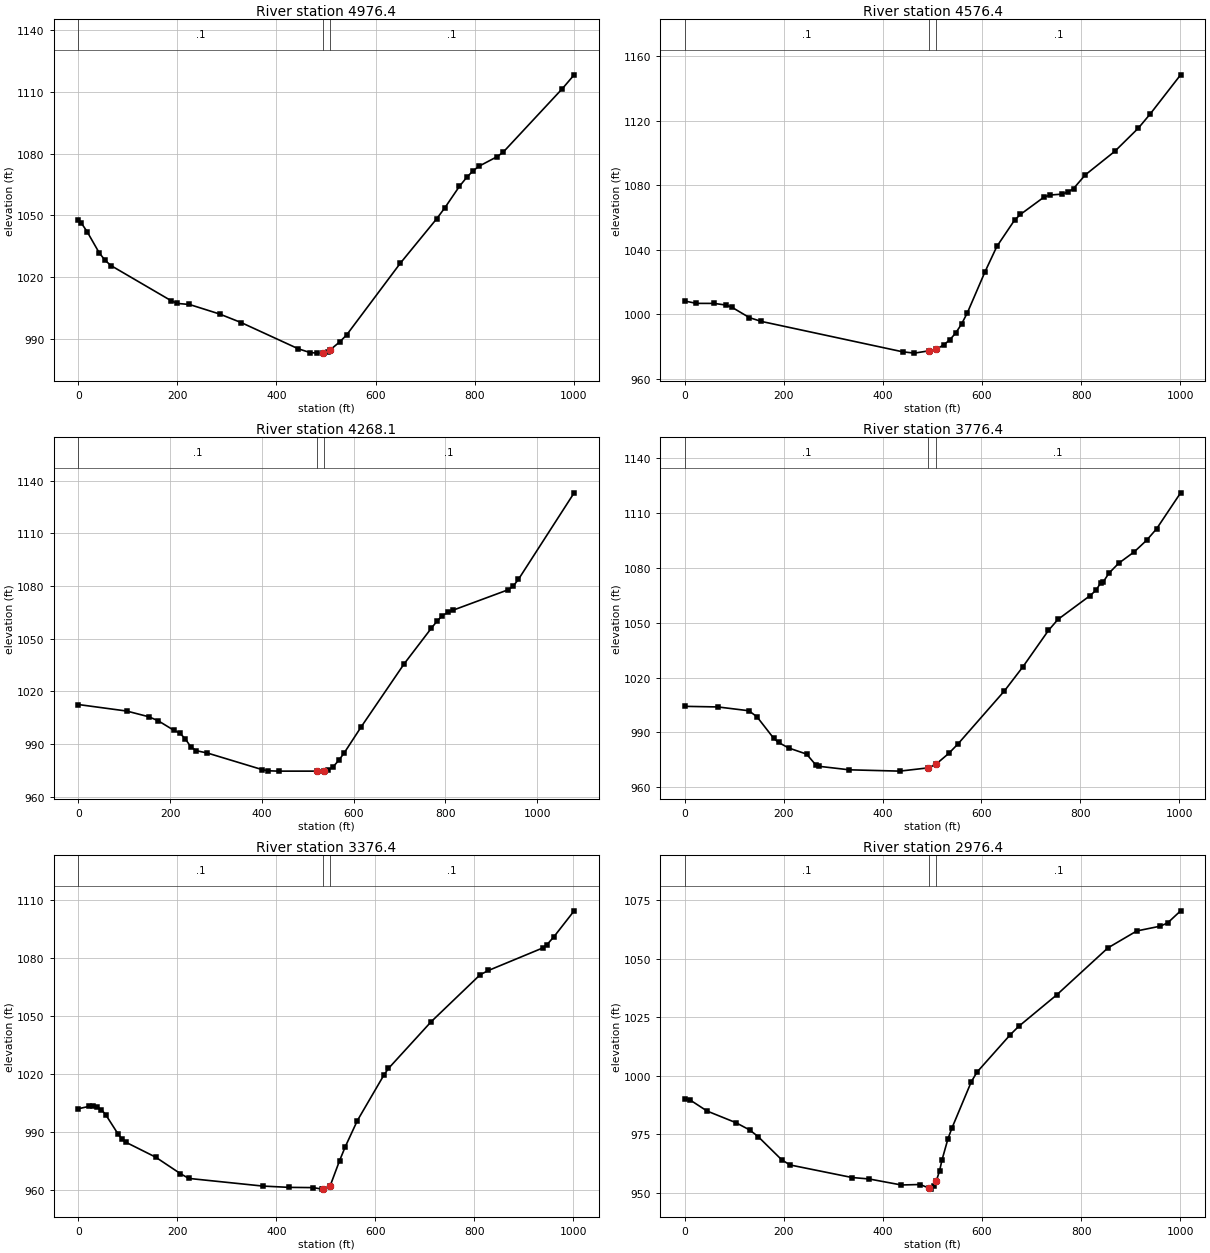
Type RM Length L Ch R = 1 ,4976.4,396.497,400,403.711
XS GIS Cut Line= 3
     1723906.025      296986.020     1723798.021      296497.133
     1723685.576      296009.573
#Sta/Elev= 30
       0 1047.88     5.4 1046.52    17.6 1042.16    41.9 1031.93    53.9 1028.20
    66.2 1025.59   187.8 1008.51   199.9 1007.24   224.3 1006.74   285.1 1002.12
   329.1  997.92   444.2  985.20   467.4  983.41   482.2  983.11   493.2  983.19
   503.9  983.84   508.2  984.65   528.3  988.69   541.8  991.99   650.1 1026.80
   723.2 1048.29   739.8 1053.65   769.5 1064.16   784.2 1068.51   796.3 1071.48
   808.5 1073.85   845.1 1078.48   857.3 1080.60   977.4 1111.63  1001.0 1118.28
#Mann= 3 , 0 , 0
       0     0.1       0   493.2   0.045       0   508.2     0.1       0
Bank Sta=   493.2,   508.2
Exp/Cntr=0.3,0.1

Type RM Length L Ch R = 1 ,4576.4,304.579,308.316,309.675
XS GIS Cut Line= 3
     1724223.205      296932.912     1724192.218      296433.372
     1724161.232      295933.832
#Sta/Elev= 30
       0 1008.26    23.4 1006.80    59.1 1006.78    82.9 1005.76    94.8 1004.45
   130.5  997.96   154.3  995.64   439.8  976.79   463.6  975.97     493  977.41
     508  978.47   522.7  981.03   534.9  984.20   546.8  988.38   558.7  993.98
   570.6 1001.06   606.3 1026.53   630.1 1042.14   665.8 1058.41   677.7 1061.95
   725.3 1072.68   737.2 1073.93   761.0 1074.49   772.9 1075.67   784.8 1077.95
   808.5 1086.41   868.0 1101.00   915.6 1115.38   939.4 1124.10  1001.0 1148.43
#Mann= 3 , 0 , 0
       0     0.1       0     493   0.045       0     508     0.1       0
Bank Sta=     493,     508
Exp/Cntr=0.3,0.1

Type RM Length L Ch R = 1 ,4268.1,509.807,491.684,461.474
XS GIS Cut Line= 3
     1724444.932      296963.690     1724500.139      296434.173
     1724485.904      295885.806
#Sta/Elev= 30
       0 1012.52   105.7 1008.80   153.4 1005.57   173.8 1003.32   207.5  997.97
   221.6  996.19   233.5  992.84   245.5  988.32   257.4  986.22   281.3  984.91
   400.6  975.47   412.6  974.80   436.5  974.60   520.6  974.60   535.6  974.74
   543.8  975.03   555.3  977.01   567.6  980.70   579.5  984.94   617.0  999.95
   710.1 1035.63   769.5 1055.96   781.4 1059.81   793.2 1063.02   805.1 1064.99
   817.0 1066.26   935.8 1077.75   947.6 1079.78   959.5 1083.82  1080.9 1133.07
#Mann= 3 , 0 , 0
       0     0.1       0   520.6   0.045       0   535.6     0.1       0
Bank Sta=   520.6,   535.6
Exp/Cntr=0.3,0.1

Type RM Length L Ch R = 1 ,3776.4,403.915,400,398.681
XS GIS Cut Line= 3
     1725179.896      296670.684     1724889.401      296263.631
     1724571.000      295874.420
#Sta/Elev= 30
       0 1004.29    66.9 1003.96   129.6 1001.88   146.0  998.56   180.1  986.72
   189.5  984.57   210.0  981.54   246.3  978.19   265.2  972.17   271.3  971.52
   332.6  969.60   434.8  968.88   492.6  970.68   507.6  972.57   533.9  978.59
   552.7  983.82   646.5 1012.76   684.0 1025.99   735.5 1045.82   754.7 1051.82
   819.9 1064.86   831.4 1067.72   841.0 1071.72   846.7 1072.52   857.9 1077.12
   877.4 1082.49   909.0 1088.75   933.8 1095.02   954.1 1101.33  1002.7 1120.99
#Mann= 3 , 0 , 0
       0     0.1       0   492.6   0.045       0   507.6     0.1       0
Bank Sta=   492.6,   507.6
Exp/Cntr=0.3,0.1

Type RM Length L Ch R = 1 ,3376.4,400.958,400,397.907
XS GIS Cut Line= 3
     1725506.094      296337.530     1725158.330      295976.550
     1724829.428      295599.466
#Sta/Elev= 30
       0 1002.12    21.6 1003.35    29.9 1003.48    38.4 1003.01    46.5 1001.66
    55.2  999.09    80.4  988.99    88.8  986.34    96.0  984.80   155.9  977.14
   206.3  968.55   223.1  966.10   372.2  962.15   425.7  961.47   474.8  961.34
   492.0  960.56   493.7  960.72   508.7  962.24   527.6  975.21   539.4  982.57
   563.7  996.02   617.9 1019.81   626.4 1022.93   712.7 1047.11   811.6 1071.38
   828.4 1073.61   937.8 1085.21   946.2 1086.81   961.1 1091.17  1001.6 1104.45
#Mann= 3 , 0 , 0
       0     0.1       0   493.7   0.045       0   508.7     0.1       0
Bank Sta=   493.7,   508.7
Exp/Cntr=0.3,0.1

Type RM Length L Ch R = 1 ,2976.4,328.17,334.616,338.938
XS GIS Cut Line= 3
     1725813.656      296050.133     1725451.382      295704.796
     1725088.802      295359.779
#Sta/Elev= 30
       0  990.23    10.6  989.69    45.0  984.96   103.0  980.01   131.1  976.87
   148.3  974.00   195.4  964.20   212.2  961.96   337.5  956.59   372.0  955.97
   437.2  953.40   475.2  953.60     493  952.07   497.7  951.63   502.8  952.89
     508  955.25   514.5  959.56   519.2  964.03   531.3  973.14   539.7  977.90
   578.5  997.51   590.1 1001.62   657.3 1017.59   674.1 1021.10   750.8 1034.53
   854.1 1054.58   912.5 1061.83   959.6 1063.86   974.7 1065.24  1001.0 1070.42
#Mann= 3 , 0 , 0
       0     0.1       0     493   0.045       0     508     0.1       0
Bank Sta=     493,     508
Exp/Cntr=0.3,0.1

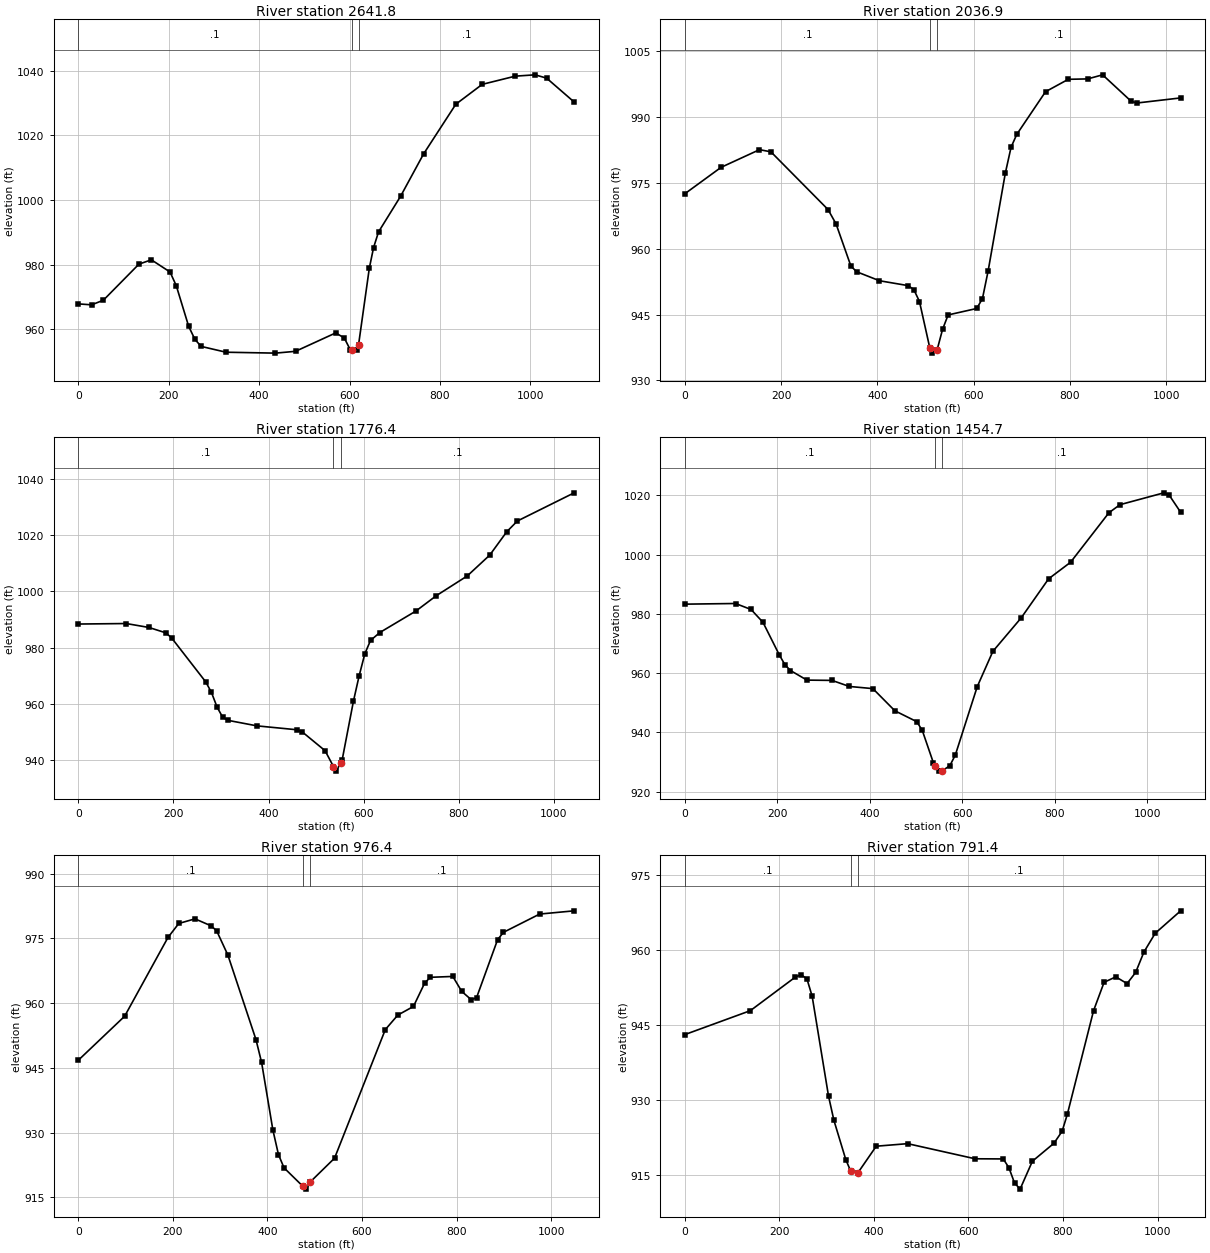
Type RM Length L Ch R = 1 ,2641.8,592.168,604.892,618.614
XS GIS Cut Line= 3
     1725979.814      295980.357     1725669.713      295451.984
     1725387.604      295058.300
#Sta/Elev= 30
       0  967.84    29.4  967.55    55.4  968.98   134.1  980.15   161.6  981.48
   202.9  977.71   216.7  973.46   244.2  960.86   258.0  956.84   271.7  954.68
   326.8  952.88   436.2  952.60   480.5  953.16   569.5  958.86   588.4  957.29
   602.1  953.53   604.9  953.60   616.1  953.46   619.9  955.09   643.8  978.89
   653.2  985.27   664.2  990.12   712.8 1001.11   763.8 1014.24   835.2 1029.64
   893.6 1035.79   966.7 1038.33  1010.7 1038.74  1036.1 1037.71  1097.0 1030.32
#Mann= 3 , 0 , 0
       0     0.1       0   604.9   0.045       0   619.9     0.1       0
Bank Sta=   604.9,   619.9
Exp/Cntr=0.3,0.1

Type RM Length L Ch R = 1 ,2036.9,257.893,260.492,263.64
XS GIS Cut Line= 3
     1726219.344      295996.116     1726211.179      295484.032
     1726182.395      294966.760
#Sta/Elev= 30
       0  972.52    75.3  978.54   155.2  982.57   178.9  982.08   297.6  968.93
   314.3  965.65   345.1  956.06   357.0  954.76   404.5  952.71   463.9  951.60
   475.8  950.71   487.6  947.97   508.9  937.48   513.0  936.22   523.9  936.82
   535.5  941.61   547.1  944.92   606.5  946.39   618.4  948.62   630.3  954.97
   666.0  977.24   677.9  983.12   689.7  986.04   749.5  995.77   796.8  998.60
   837.0  998.69   868.1  999.62   927.6  993.58   939.5  993.20  1030.2  994.36
#Mann= 3 , 0 , 0
       0     0.1       0   508.9   0.045       0   523.9     0.1       0
Bank Sta=   508.9,   523.9
Exp/Cntr=0.3,0.1

Type RM Length L Ch R = 1 ,1776.4,323.048,321.653,320.275
XS GIS Cut Line= 3
     1726358.019      295917.323     1726418.319      295376.710
     1726469.530      294880.851
#Sta/Elev= 30
       0  988.41   100.7  988.59   148.5  987.19   184.3  985.26   196.3  983.43
   268.0  967.79   279.9  964.06   291.9  958.77   303.8  955.17   315.7  954.10
   375.5  952.17   459.1  950.79   471.0  949.99   518.8  943.33   536.5  937.67
   542.7  936.06   551.5  939.12   554.7  940.04   578.5  961.02   590.5  970.05
   602.4  977.84   614.3  982.56   633.9  985.39   709.8  993.04   752.9  998.53
   817.8 1005.54   865.0 1012.94   900.8 1021.26   923.0 1025.07  1042.5 1035.11
#Mann= 3 , 0 , 0
       0     0.1       0   536.5   0.045       0   551.5     0.1       0
Bank Sta=   536.5,   551.5
Exp/Cntr=0.3,0.1

Type RM Length L Ch R = 1 ,1454.7,480.4,478.347,475.725
XS GIS Cut Line= 3
     1726711.010      295926.778     1726738.896      295364.198
     1726754.503      294855.042
#Sta/Elev= 30
       0  983.26   109.7  983.48   143.4  981.46   169.1  977.14   204.8  966.04
   216.7  962.82   228.6  960.88   264.2  957.64   318.5  957.54   356.0  955.50
   406.9  954.77   454.4  947.30   502.0  943.61   513.8  940.66   537.6  929.85
   542.1  928.75   549.5  926.94   557.1  927.09   573.3  928.74   585.2  932.34
   632.7  955.44   666.5  967.34   727.7  978.62   787.1  991.81   834.6  997.39
   917.7 1014.11   941.5 1016.81  1036.5 1020.81  1048.4 1019.93  1072.7 1014.27
#Mann= 3 , 0 , 0
       0     0.1       0   542.1   0.045       0   557.1     0.1       0
Bank Sta=   542.1,   557.1
Exp/Cntr=0.3,0.1

Type RM Length L Ch R = 1 ,976.4,185.013,185,185.724
XS GIS Cut Line= 3
     1727229.842      295895.976     1727211.357      295413.851
     1727171.160      294848.894
#Sta/Elev= 30
       0  946.78    98.0  956.98   189.6  975.23   212.5  978.48   246.8  979.55
   281.1  977.92   292.7  976.76   316.4  971.14   375.8  951.56   387.7  946.26
   411.5  930.64   423.4  924.89   435.2  921.83     475  917.56   482.5  916.90
     490  918.50   542.0  924.07   649.4  953.88   675.9  957.25   708.9  959.24
   732.7  964.67   744.6  966.00   792.2  966.20   811.1  962.73   831.4  960.79
   842.5  961.30   887.0  974.74   899.4  976.43   975.9  980.66  1048.9  981.41
#Mann= 3 , 0 , 0
       0     0.1       0     475   0.045       0     490     0.1       0
Bank Sta=     475,     490
Exp/Cntr=0.3,0.1

Type RM Length L Ch R = 1 ,791.4,792.596,791.395,789.366
XS GIS Cut Line= 3
     1727395.603      295706.535     1727377.118      295224.410
     1727336.921      294659.452
#Sta/Elev= 30
       0  943.12   138.7  947.92   233.8  954.64   245.7  955.12   258.3  954.31
   269.4  950.81   304.1  930.77   315.5  925.92   340.7  918.04   350.9  915.79
   365.9  915.39   405.0  920.76   471.4  921.27   614.2  918.24   673.7  918.21
   685.6  916.46   697.5  913.40   709.3  912.16   735.3  917.75   780.9  921.35
   798.2  923.75   809.3  927.18   864.8  947.94   887.0  953.60   911.8  954.69
   935.6  953.34   953.7  955.57   971.3  959.67   995.1  963.42  1048.9  967.92
#Mann= 3 , 0 , 0
       0     0.1       0   350.9   0.045       0   365.9     0.1       0
Bank Sta=   350.9,   365.9
Exp/Cntr=0.3,0.1